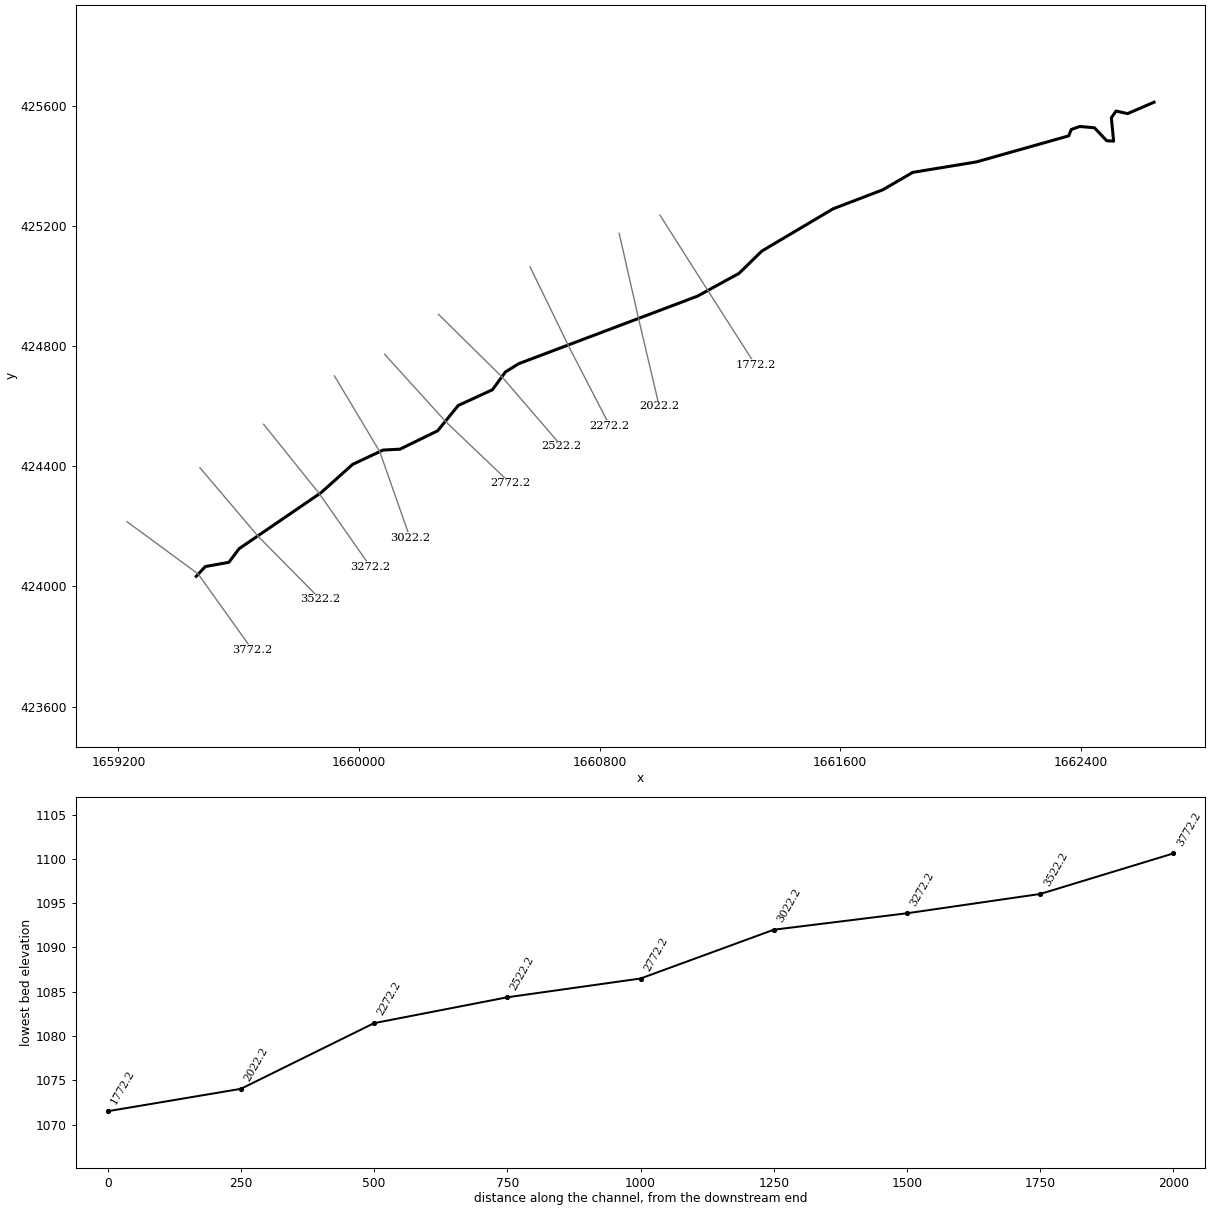
--- MORRISRN.prj (project) ---

Proj Title=MORRISRN
Current Plan=p01
Geom File=g01
Flow File=f01
Plan File=p01
DSS Export Rating Curves=0
DSS Export Rating Curve Sorted=0
DSS Export Volume Flow Curves=0
DXF OffsetX=0
DXF OffsetY=0
DXF ScaleX=0
DXF ScaleY=0

--- MORRISRN.p01 (plan) ---

Plan Title=Floodplain
Program Version=4.00
Geom File=g01
Flow File=f01
K Sum by GR=0
Std Step Tol=0.01
Critical Tol=0.01
Num of Std Step Trials=20
Max Error Tol=0.3
Flow Tol Ratio=0.001
Split Flow NTrial=30
Split Flow Tol=0.02
Split Flow Ratio=0.02
Log Output Level=0
Friction Slope Method=1
Unsteady Friction Slope Method=2
Unsteady Bridges Friction Slope Method=1
Global Log Level=0
CheckData=False
Run HTab=0
Run UNet=0
Run PostProcess=0
UNET Theta=0
UNET Theta Warmup=0
UNET ZTol=0
UNET ZSATol=0
UNET MxIter=0
UNET MaxInSteps=0
UNET DtIC=0
UNET DtMin=0
UNET MaxCRTS=0
UNET WFStab=0
UNET SFStab=0
UNET WFX=0
UNET SFX=0
UNET DSS MLevel=0
UNET DZMax Abort=0
UNET Convert EG Bridges=0
UNET Use Existing IB Tables=0
UNET Froude Limit=0
UNET Froude Power=0
Write IC File=0
Echo Input=False
Echo Output=False
Write Detailed=0

--- MORRISRN.f01 (steady flow) ---

Flow Title=Flow
Program Version=4.00
Number of Profiles=1
Profile Names=F01pct
River Rch & RM=MORRISRN,Main      ,3772.2
567.9047
River Rch & RM=MORRISRN,Main      ,3522.2
568.6129
River Rch & RM=MORRISRN,Main      ,3272.2
571.6568
River Rch & RM=MORRISRN,Main      ,2772.2
576.6847
River Rch & RM=MORRISRN,Main      ,2522.2
584.2642
River Rch & RM=MORRISRN,Main      ,2272.2
623.9673
River Rch & RM=MORRISRN,Main      ,2022.2
627.5645
River Rch & RM=MORRISRN,Main      ,1772.2
630.9579
Boundary for River Rch & Prof#=MORRISRN,Main      ,1
Up Type=0
Dn Type=3
Dn Slope=0.016488

--- MORRISRN.g01 (geometry) ---

Geom Title=Geometry
Program Version=4.00

River Reach=MORRISRN     ,Main
Reach XY= 30
     1659458.913      424033.901     1659488.994      424066.489
     1659567.205      424080.527     1659601.297      424125.899
     1659873.282      424312.153     1659978.818      424406.909
     1660080.091      424454.538     1660136.243      424457.546
     1660261.331      424518.711     1660329.766      424602.939
     1660443.574      424655.581     1660486.941      424714.992
     1660531.562      424742.566     1661124.915      424967.173
     1661263.540      425043.379     1661339.245      425117.580
     1661576.386      425258.461     1661741.332      425321.631
     1661841.101      425379.789     1662052.673      425414.633
     1662359.503      425501.367     1662368.026      425522.424
     1662396.102      425532.702     1662444.984      425528.440
     1662486.095      425485.073     1662508.906      425483.820
     1662501.386      425561.780     1662516.928      425584.091
     1662555.282      425575.568     1662643.385      425613.580

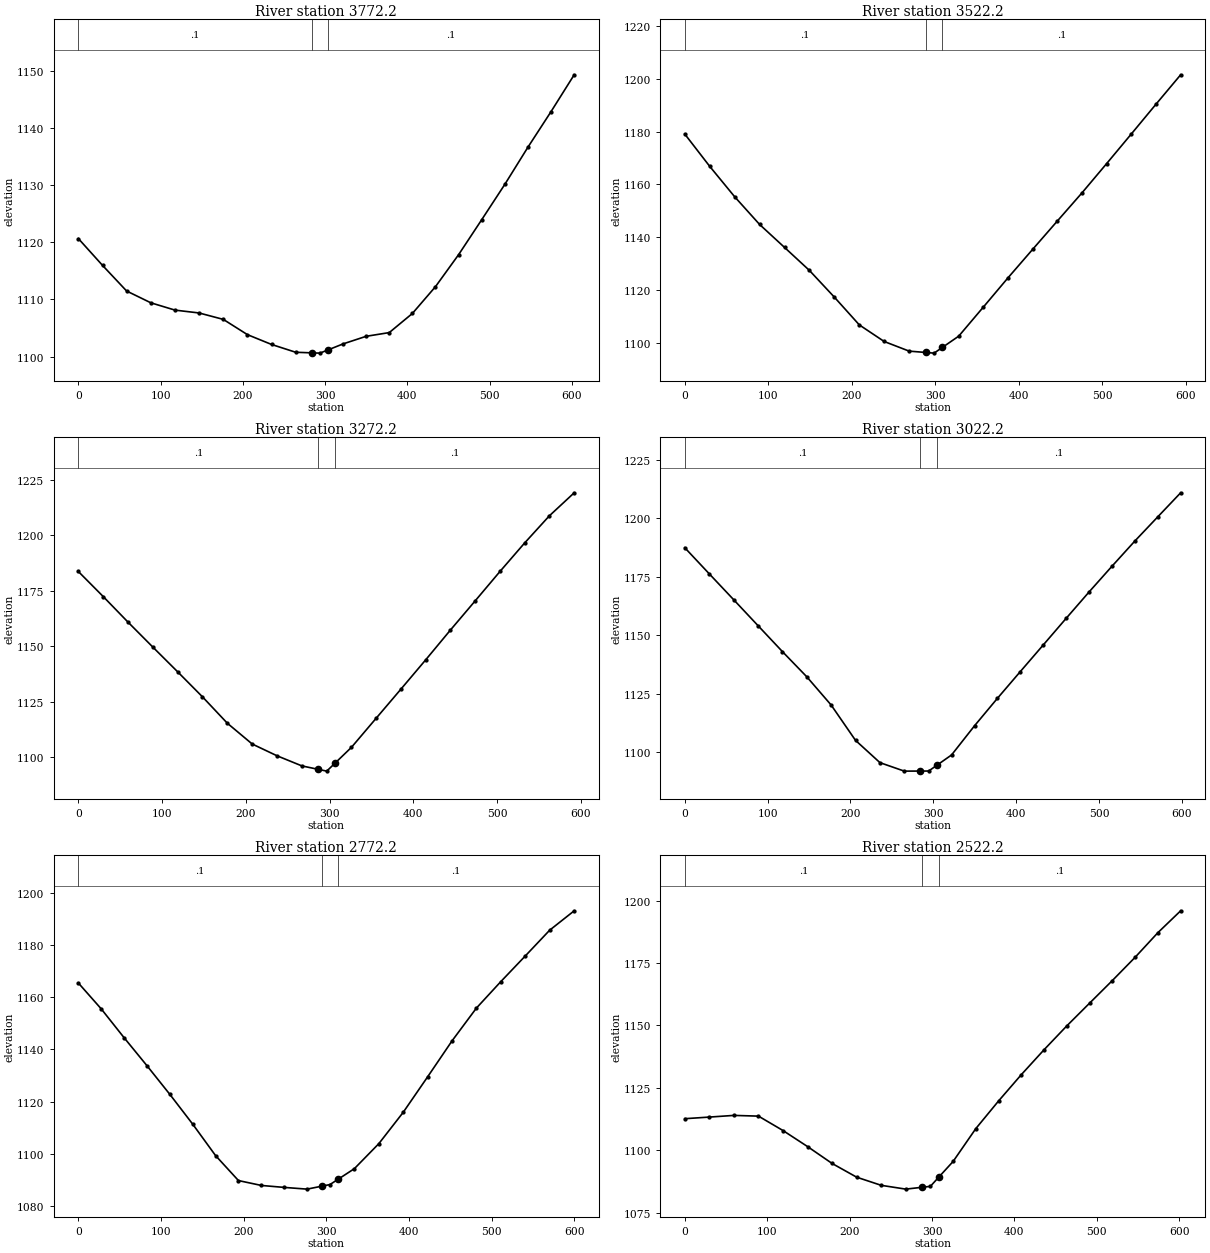
Type RM Length L Ch R = 1 ,3772.2,254.6,250,253
XS GIS Cut Line= 3
     1659228.644      424215.913     1659465.112      424041.738
     1659644.529      423790.039
#Sta/Elev= 24
       0 1120.65    29.4 1115.96    58.7 1111.48    88.1 1109.42   117.5 1108.14
   146.8 1107.64   176.2 1106.52   205.6 1103.85   235.0 1102.13   264.3 1100.77
   283.7 1100.67   293.7 1100.62   303.7 1101.19   321.8 1102.23   349.9 1103.56
   378.0 1104.21   406.1 1107.55   434.2 1112.24   462.3 1117.83   490.4 1123.94
   518.5 1130.12   546.6 1136.62   574.7 1142.84   602.8 1149.27
#Mann= 3 , 0 , 0
       0     0.1       0   283.7   0.045       0   303.7     0.1       0
Bank Sta=283.7,303.7
Exp/Cntr=0.3,0.1

Type RM Length L Ch R = 1 ,3522.2,250.3,250,245.5
XS GIS Cut Line= 3
     1659470.878      424395.815     1659663.926      424167.905
     1659871.288      423957.447
#Sta/Elev= 23
       0 1179.07    29.9 1166.82    59.7 1155.33    89.6 1144.82   119.5 1136.11
   149.3 1127.39   179.2 1117.26   209.1 1106.74   238.9 1100.45   268.8 1096.80
   288.7 1096.29   298.7 1096.04   308.7 1098.22   328.2 1102.47   357.8 1113.52
   387.3 1124.60   416.9 1135.41   446.4 1146.12   476.0 1156.82   505.5 1167.90
   535.0 1179.10   564.6 1190.40   594.1 1201.53
#Mann= 3 , 0 , 0
       0     0.1       0   288.7   0.045       0   308.7     0.1       0
Bank Sta=288.7,308.7
Exp/Cntr=0.3,0.1

Type RM Length L Ch R = 1 ,3272.2,252.8,250,241.9
XS GIS Cut Line= 3
     1659683.045      424540.241     1659868.399      424308.601
     1660037.663      424066.337
#Sta/Elev= 23
       0 1183.76    29.7 1172.48    59.3 1160.97    89.0 1149.71   118.7 1138.56
   148.3 1127.30   178.0 1115.42   207.7 1106.06   237.3 1100.77   267.0 1096.21
   286.7 1094.65   296.7 1093.86   306.7 1097.49   326.2 1104.57   355.8 1117.71
   385.3 1130.78   414.9 1143.98   444.4 1157.38   474.0 1170.54   503.6 1183.77
   533.1 1196.62   562.6 1208.83   592.2 1219.18
#Mann= 3 , 0 , 0
       0     0.1       0   286.7   0.045       0   306.7     0.1       0
Bank Sta=286.7,306.7
Exp/Cntr=0.3,0.1

Type RM Length L Ch R = 1 ,3022.2,244.4,250,261
XS GIS Cut Line= 3
     1659918.206      424701.687     1660069.119      424448.865
     1660169.664      424161.765
#Sta/Elev= 24
       0 1187.39    29.4 1176.30    58.9 1165.24    88.3 1154.16   117.8 1143.06
   147.2 1132.31   176.7 1120.22   206.1 1105.14   235.6 1095.62   265.0 1092.00
   284.4 1092.03   294.4 1092.04   304.4 1094.52   322.1 1098.92   349.8 1111.37
   377.4 1123.08   405.0 1134.48   432.7 1145.85   460.4 1157.24   488.0 1168.48
   515.7 1179.48   543.3 1190.24   571.0 1200.58   598.6 1210.84
#Mann= 3 , 0 , 0
       0     0.1       0   284.4   0.045       0   304.4     0.1       0
Bank Sta=284.4,304.4
Exp/Cntr=0.3,0.1

Type RM Length L Ch R = 1 ,2772.2,247.9,250,244.7
XS GIS Cut Line= 3
     1660084.993      424773.864     1660289.326      424548.262
     1660502.903      424344.175
#Sta/Elev= 24
       0 1165.44    27.7 1155.52    55.3 1144.50    83.0 1133.77   110.7 1122.78
   138.4 1111.36   166.0 1099.34   193.7 1089.77   221.4 1087.90   249.0 1087.15
   276.7 1086.49   294.4 1087.61   304.4 1088.24   314.4 1090.30   333.9 1094.32
   363.5 1103.90   393.0 1115.90   422.6 1129.52   452.1 1143.28   481.6 1155.84
   511.2 1166.00   540.7 1175.79   570.2 1185.66   599.8 1193.07
#Mann= 3 , 0 , 0
       0     0.1       0   294.4   0.045       0   314.4     0.1       0
Bank Sta=294.4,314.4
Exp/Cntr=0.3,0.1

Type RM Length L Ch R = 1 ,2522.2,258.1,250,244.9
XS GIS Cut Line= 3
     1660264.100      424906.974     1660476.109      424697.561
     1660673.988      424467.200
#Sta/Elev= 24
       0 1112.60    29.8 1113.25    59.6 1113.92    89.4 1113.63   119.2 1107.85
   149.0 1101.42   178.8 1094.65   208.6 1089.15   238.4 1085.89   268.2 1084.37
     288 1085.11   298.0 1085.48     308 1089.10   325.6 1095.46   353.2 1108.65
   380.8 1119.72   408.4 1130.26   436.0 1140.25   463.6 1149.81   491.2 1158.90
   518.8 1167.96   546.5 1177.30   574.1 1187.16   601.7 1195.92
#Mann= 3 , 0 , 0
       0     0.1       0     288   0.045       0     308     0.1       0
Bank Sta=288,308
Exp/Cntr=0.3,0.1

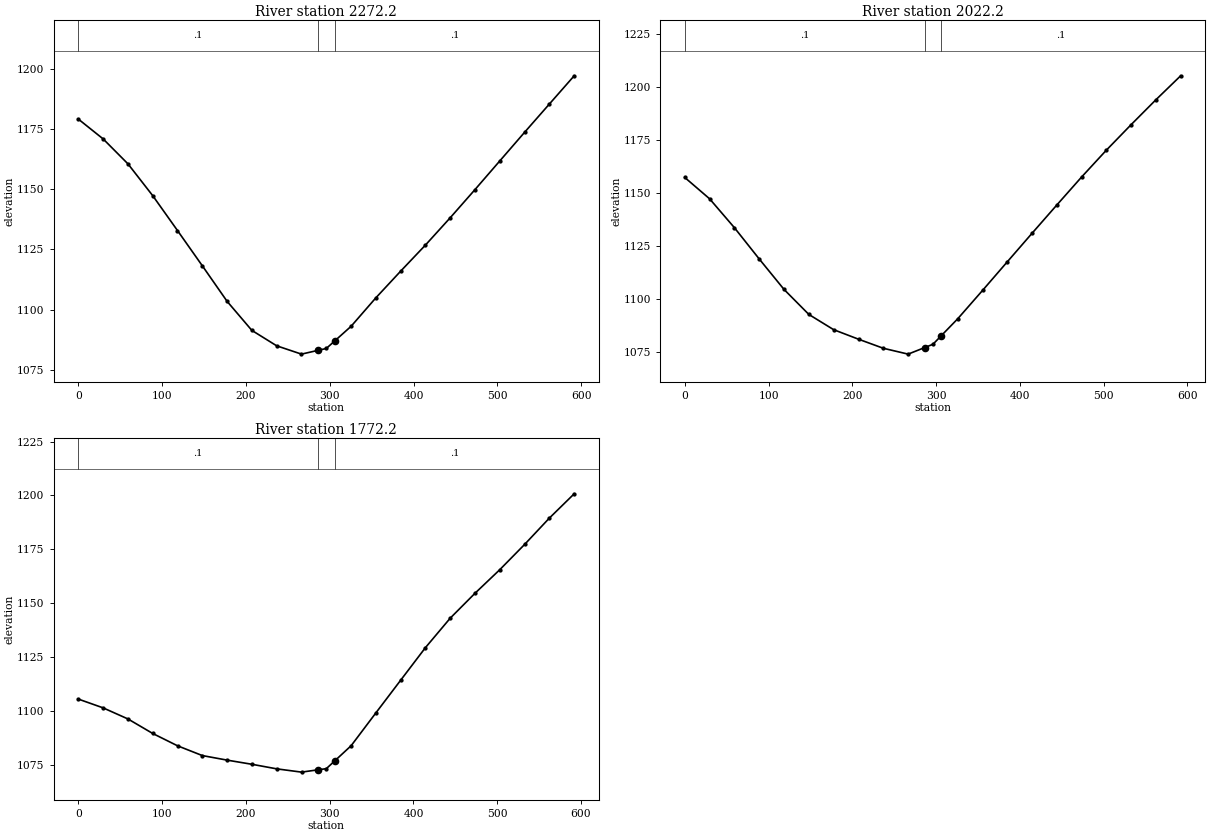
Type RM Length L Ch R = 1 ,2272.2,255.5,250,243.6
XS GIS Cut Line= 3
     1660568.660      425065.076     1660697.841      424799.009
     1660833.383      424536.121
#Sta/Elev= 23
       0 1179.15    29.6 1170.91    59.2 1160.54    88.7 1147.34   118.3 1132.82
   147.9 1118.18   177.5 1103.38   207.0 1091.32   236.6 1084.91   266.2 1081.45
   285.8 1083.01   295.8 1083.80   305.8 1086.91   325.4 1093.02   354.9 1104.84
   384.5 1115.93   414.1 1126.79   443.7 1138.16   473.2 1149.85   502.8 1161.77
   532.4 1173.68   562.0 1185.44   591.5 1197.14
#Mann= 3 , 0 , 0
       0     0.1       0   285.8   0.045       0   305.8     0.1       0
Bank Sta=285.8,305.8
Exp/Cntr=0.3,0.1

Type RM Length L Ch R = 1 ,2022.2,241.2,250,258.2
XS GIS Cut Line= 3
     1660864.922      425176.694     1660930.534      424887.841
     1660998.248      424599.988
#Sta/Elev= 23
       0 1157.35    29.6 1147.30    59.2 1133.68    88.9 1118.89   118.5 1104.53
   148.1 1092.75   177.7 1085.56   207.4 1081.07   237.0 1076.79   266.6 1074.03
   286.2 1077.10   296.2 1078.67   306.2 1082.73   325.8 1090.70   355.4 1104.06
   384.9 1117.54   414.5 1131.02   444.1 1144.37   473.6 1157.54   503.2 1170.22
   532.8 1182.27   562.4 1194.02   591.9 1205.31
#Mann= 3 , 0 , 0
       0     0.1       0   286.2   0.045       0   306.2     0.1       0
Bank Sta=286.2,306.2
Exp/Cntr=0.3,0.1

Type RM Length L Ch R = 1 ,1772.2,1714.7,1772.2,1753.8
XS GIS Cut Line= 3
     1661000.616      425237.261     1661159.049      424987.174
     1661318.145      424737.924
#Sta/Elev= 23
       0 1105.42    29.6 1101.34    59.2 1096.20    88.8 1089.45   118.4 1083.73
   148.0 1079.19   177.6 1077.07   207.2 1075.14   236.8 1073.02   266.4 1071.50
     286 1072.57   296.0 1073.11     306 1076.71   325.6 1083.76   355.2 1099.04
   384.8 1114.22   414.3 1129.32   443.9 1143.01   473.5 1154.58   503.0 1165.50
   532.6 1177.21   562.2 1189.47   591.8 1200.74
#Mann= 3 , 0 , 0
       0     0.1       0     286   0.045       0     306     0.1       0
Bank Sta=286,306
Exp/Cntr=0.3,0.1