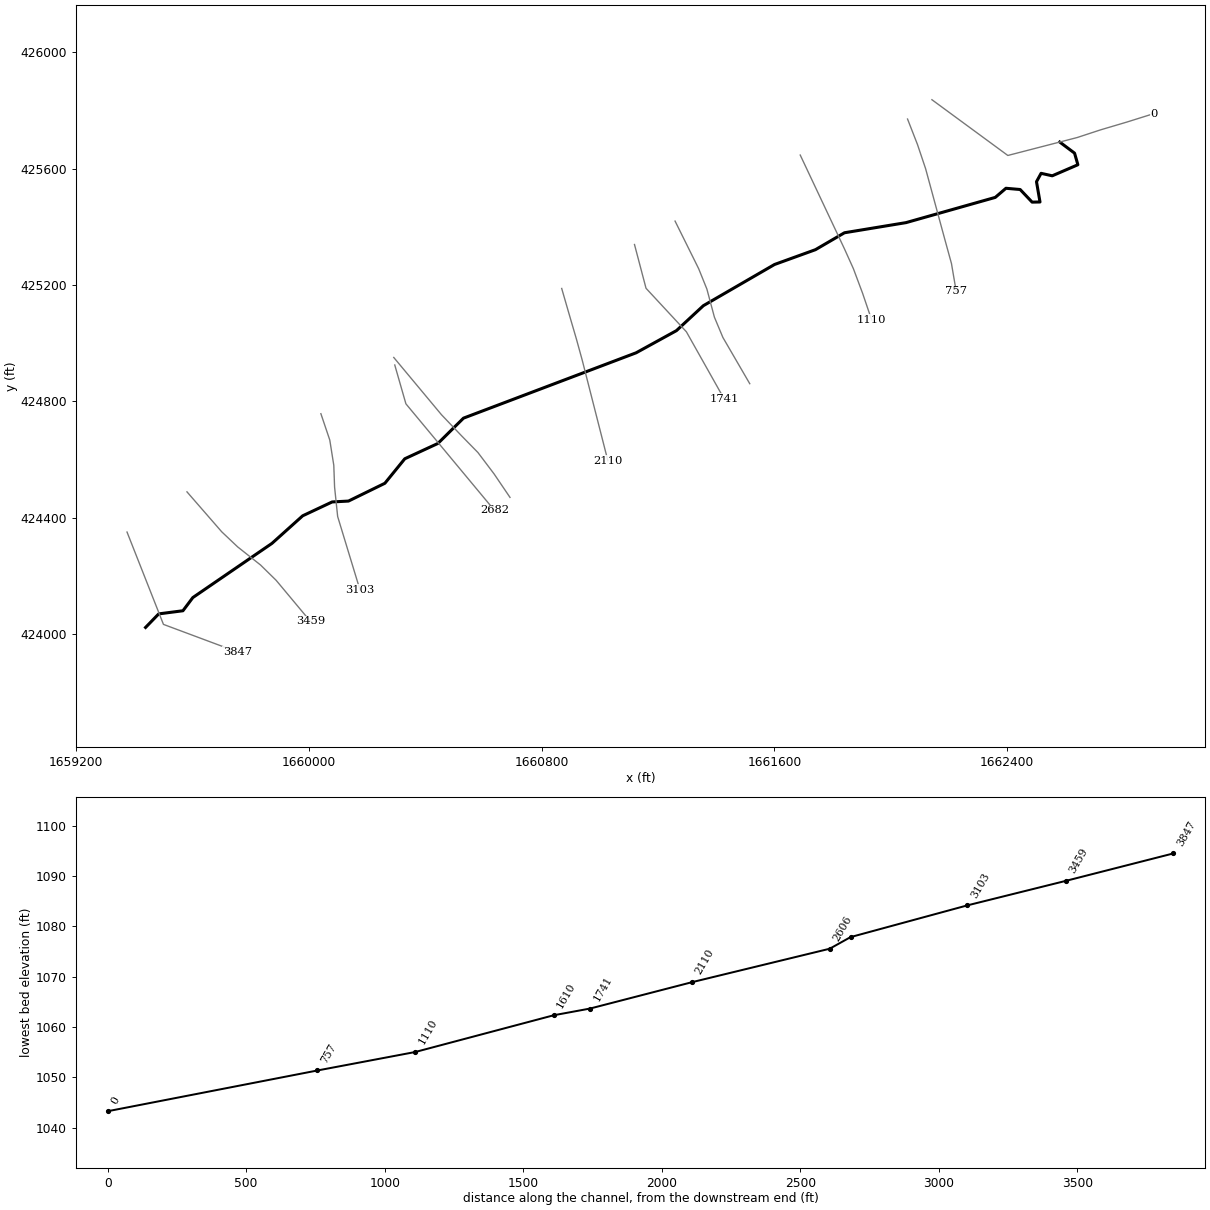
--- MORRISRN.prj (project) ---

Proj Title=MORRISRN
Current Plan=p01
Default Exp/Contr=0,0
English Units
Geom File=g01
Flow File=f01
Plan File=p01
BEGIN DESCRIPTION:
---------- MODELED AS PART OF WVEMD CTP PROGRAM, 2023----------
Stream Name: Morris Run
Flood Zone:  AFH
Wetzel County, WV
HEC-RAS Version: RAS 6.3
Vertical Datum: NAVD88
Projection: NAD 1983 StatePlane West Virginia S FIPS 4702 (US Feet)
Terrain: 1-meter West Virginia FEMA R3 South Central (collected 2018-2020)
Land Use: 2019 NLCD
Hydrologic Method:
WV SIR2010-5033 regression equations
Additional Model Notes:
KWSE tie-in with MILLERFK
END DESCRIPTION:
DSS Export Rating Curves= 0
DSS Export Rating Curve Sorted= 0
DSS Export Volume Flow Curves= 0
DXF OffsetX= 0
DXF OffsetY= 0
DXF ScaleX= 0
DXF ScaleY= 0

--- MORRISRN.p01 (plan) ---

Plan Title=Floodplain
Program Version=6.31
Short Identifier=Floodplain
Geom File=g01
Flow File=f01
Subcritical Flow
K Sum by GR= 0
Std Step Tol= 0.01
Critical Tol= 0.01
Num of Std Step Trials= 20
Max Error Tol= 0.3
Flow Tol Ratio= 0.001
Split Flow NTrial= 30
Split Flow Tol= 0.02
Split Flow Ratio= 0.02
Log Output Level= 0
Friction Slope Method= 1
Unsteady Friction Slope Method= 2
Unsteady Bridges Friction Slope Method= 1
Parabolic Critical Depth
Global Vel Dist= 0 , 0 , 0
Global Log Level= 0
CheckData=True
Encroach Param=-1 ,0,0, 0
Mapping Interval=1HOUR
Computation Time Step Use Courant=        0
Computation Time Step Use Time Series=    0
Computation Time Step Count To Double=0
Computation Time Step Max Doubling=0
Computation Time Step Max Halving=0
Computation Time Step Residence Courant=0
Run HTab= 0
Run UNet= 0
Run Sediment= 0
Run PostProcess= 0
Run WQNet= 0
Run RASMapper= 0
UNET Theta= 0
UNET Theta Warmup= 0
UNET ZTol= 0
UNET ZSATol= 0
UNET MxIter= 0
UNET Max Iter WO Improvement= 0
UNET MaxInSteps= 0
UNET DtIC= 0
UNET DtMin= 0
UNET MaxCRTS= 0
UNET WFStab= 0
UNET SFStab= 0
UNET WFX= 1
UNET SFX= 1
UNET Gravity=32.17405
UNET 1D Methodology=Finite Difference
UNET DSS MLevel= 1
UNET Pardiso=0
UNET DZMax Abort= 0
UNET Use Existing IB Tables= 0
UNET Froude Reduction=False
UNET Froude Limit= 0
UNET Froude Power= 0
UNET D1 Cores= 0
UNET WindReference=Eulerian
UNET WindDragFormulation=Hsu (1988)
UNET D2 Coriolis=0
UNET D2 Cores= 0
UNET D2 Theta= 1
UNET D2 Theta Warmup= 1
UNET D2 Z Tol= 0.01
UNET D2 Volume Tol= 0.01
UNET D2 Max Iterations= 20
UNET D2 Equation= 0
UNET D2 RampUpFraction=0.1
UNET D2 TimeSlices= 1
UNET D2 Turbulence Formulation=Non-Conservative (original)
UNET D2 Eddy Viscosity=0.3
UNET D2 Transverse Eddy Viscosity=0.1
UNET D2 Smagorinsky Mixing=0
UNET D2 BCVolumeCheck=0
UNET D2 Cores=0
UNET D2 SolverType=PARDISO (Direct)
UNET D2 Minimum Iterations= 3
UNET D2 Maximum Iterations= 30
UNET D2 Restart Number= 10
UNET D2 Relaxation Coeff=1.3
UNET D2 SOR Precondition Iterations= 10
UNET D2 ILUT Maximum Fill= 8
UNET D2 ILUT Tolerance=1E-08
UNET D2 Convergence Tolerance=0.00001
UNET D1D2 MaxIter= 0
UNET D1D2 ZTol=0.01
UNET D1D2 QTol=0.1
UNET D1D2 MinQTol=1
Write IC File= 0
Write IC File at Fixed DateTime=0
Write IC File at Sim End=0
Echo Input=False
Echo Parameters=False
Echo Output=False
Write Detailed= 0
HDF Write Warmup=0
HDF Write Time Slices=0
HDF Flush=0
HDF Compression= 1
HDF Chunk Size= 1
HDF Spatial Parts= 1
HDF Use Max Rows=0
HDF Fixed Rows= 1
Calibration Method= 0
Calibration Iterations= 20
Calibration Max Change=0.05
Calibration Tolerance=0.2
Calibration Maximum=1.5
Calibration Minimum=0.5
Calibration Optimization Method= 1
WQ AD Non Conservative
WQ ULTIMATE=-1
WQ Max Comp Step=1HOUR
WQ Output Interval=15MIN
WQ Output Selected Increments= 0
WQ Create Restart=0
WQ Fixed Restart=0
WQ System Summary=0
WQ Write To DSS=0
Sorting and Armoring Iterations= 10
XS Update Threshold= 0.02
Bed Roughness Predictor= 0
Hydraulics Update Threshold= 0.02
Energy Slope Method= 1
Volume Change Method= 1
Sediment Retention Method= 0
Sediment TS Multiplier= 1
Warm Up Method= 0
XS Weighting Method= 0
Number of US Weighted Cross Sections= 1
Number of DS Weighted Cross Sections= 1
Upstream XS Weight=0
Main XS Weight=1
Downstream XS Weight=0
Number of DS XS's Weighted with US Boundary= 1
Upstream Boundary Weight= 1
Weight of XSs Associated with US Boundary= 0
Number of US XS's Weighted with DS Boundary= 1
Downstream Boundary Weight= 0.5
Weight of XSs Associated with DS Boundary= 0.5
Percentile Method= 0
Sediment Output Level= 3
Mass or Volume Output= 0
Output Increment Type= 1
Profile and TS Output Increment= 1
Transport Output Increment 1
XS Output Flag= 0
XS Output Increment= 10
Read HDF5 Sediment Hotstart= 0
Sediment Hotstart Type= 0
Write Gradation File= 0
Read Gradation Hotstart= 0
Write HDF5 File= 1
Write Binary Output= 1
Write DSS Sediment File= 0
DSS Sediment Output Type= 1
SV Curve= 0
Specific Gage Flag= 0
Subcell Erosion Methods= 0
Subcell Deposition Methods= 0
Advection Scheme= 1
Matrix Solver= 0
Implicit Weighting Factor= 1
Maximum Outer Loop Convergence Iterations= 5
Convergence Maximum Absolute= 0.001
Convergence RMSE= 0.0001
Grain Fractions Max Abs Error= 0.001
Max Subgrid Regions= 1
Max Subgrid Length Scale= 3.402823E+38
Initial Layer Thickness= 3.402823E+38
Min Layer Thickness= 3.402823E+38
Max Layer Thickness= 3.402823E+38
Number of Layers= 5

--- MORRISRN.f01 (steady flow) ---

Flow Title=Flow
Program Version=6.30
Number of Profiles= 1
Profile Names=F01pct
River Rch & RM=MORRISRN,Main            ,3847
     701
River Rch & RM=MORRISRN,Main            ,0
    1350
Boundary for River Rch & Prof#=MORRISRN,Main            , 1
Up Type= 0
Dn Type= 1
Dn Known WS=1049.1
DSS Import GetInterval= 0
DSS Import GetPeak= 0
DSS Import FillOption= 0

--- MORRISRN.g01 (geometry) ---

Geom Title=Geometry
Program Version=6.31

River Reach=MORRISRN        ,Main
Reach XY= 30
1659438.75039878424023.1476127061659483.93971235424069.772965387
     1659567.205424080.5269999951659601.29700002424125.899000004
1659873.28200002424312.1530000121659978.81800002424406.908999994
1660080.09100002424454.538000032     1660136.243424457.546000004
1660261.33100002424518.710999995     1660329.766424602.938999996
1660443.57400002424655.5810000151660531.56200001      424742.566
1661124.91500001424967.1729999931661263.54000004425043.379000008
1661356.04000001425129.1110000161661600.70200002425270.744000018
1661741.33200002425321.630999997     1661841.101425379.789000005
1662052.67299999425414.6330000011662359.50300002425501.367000014
     1662396.102425532.702000037     1662444.984425528.440000013
1662486.09500001425485.0729999991662513.16800001425485.575000003
1662501.13500002425555.262999997     1662516.928425584.091000006
1662555.28200001425575.5680000041662643.38502795425613.579797328
1662631.92800002425653.4580000191662581.00087489425691.610263094

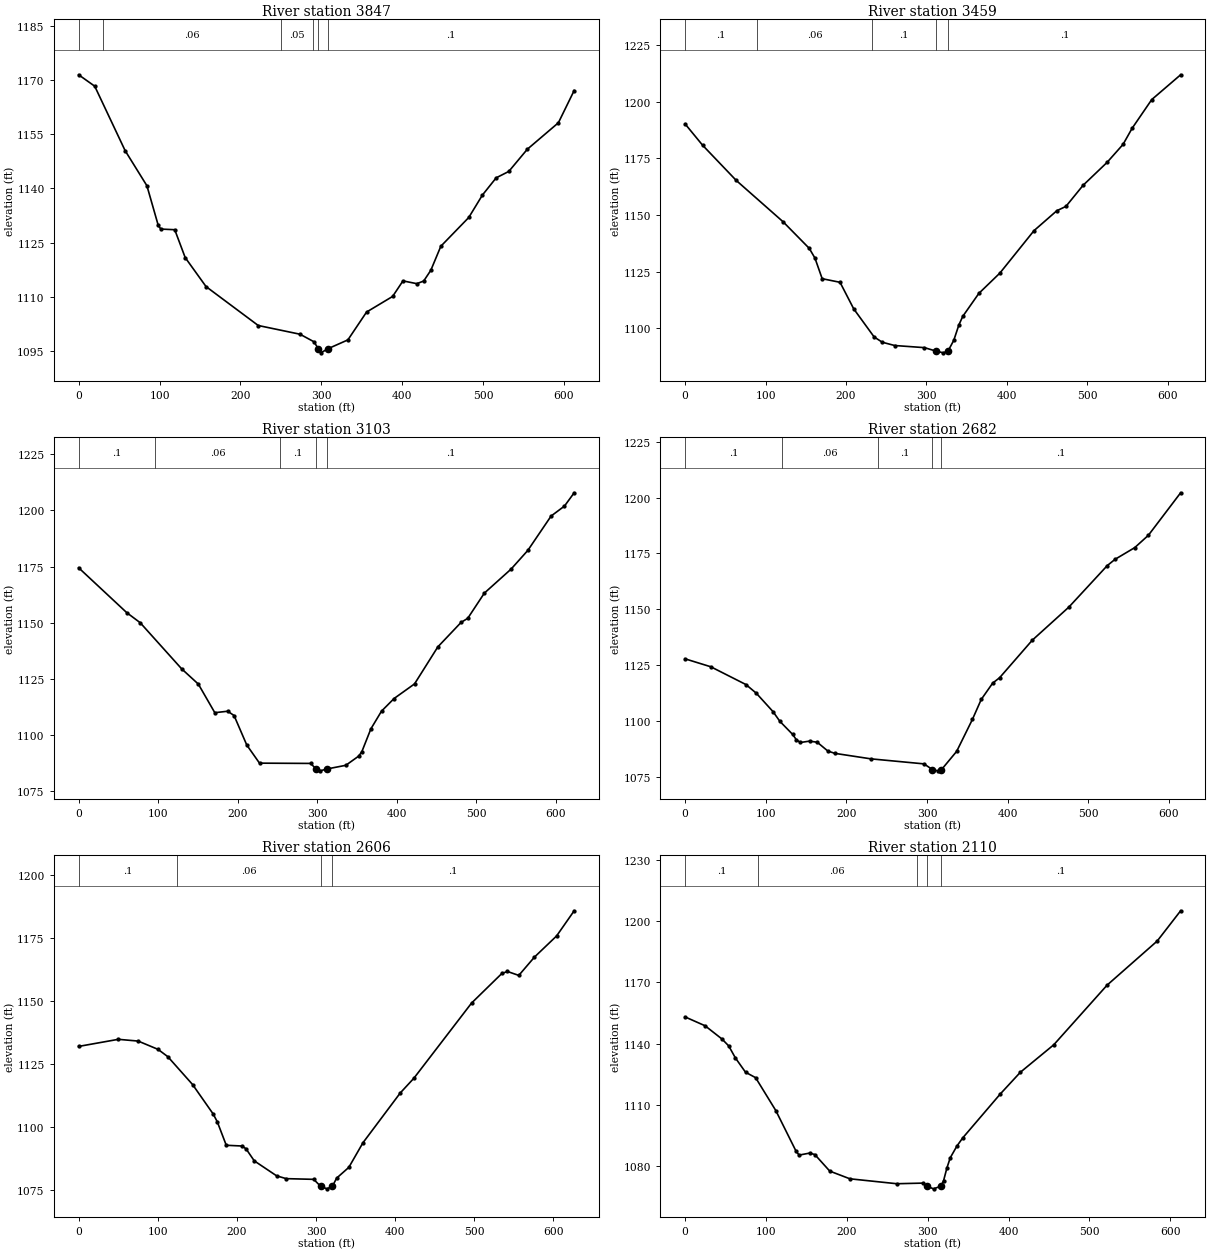
Type RM Length L Ch R = 1 ,3847    ,383.6,387.5,390.3
XS GIS Cut Line= 3
1659375.01158563 424351.088323251659500.21190704424033.661245743
1659754.40649898423938.812517404
#Sta/Elev= 30
       0 1171.39    19.9 1168.23    57.5  1150.4    84.4  1140.7    98.4 1129.74
   101.6 1128.72   118.8 1128.54   131.7 1120.84   157.5 1112.81     222 1102.05
   273.6 1099.64   290.8 1097.56  296.231095.649   299.4 1094.49     308 1095.61
   332.8 1098.07   355.9 1105.77   388.1 1110.09   400.9 1114.39     418 1113.62
   426.5 1114.35   435.3 1117.31   447.7 1123.97   482.2 1131.92   499.1 1138.13
   516.1 1142.89   531.7 1144.66   554.6  1150.8     593 1158.12   612.5 1167.04
#Mann= 6 ,-1,0
       0      .1       0      30     .06       0     250     .05       0
     290      .1       0  296.23    .045       0     308      .1       0
Bank Sta=296.23,308
XS Rating Curve= 0 ,0
Exp/Cntr(USF)=0,0
Exp/Cntr=0.3,0.1

Type RM Length L Ch R = 1 ,3459    ,362.5,356.4,351.8
XS GIS Cut Line= 6
1659581.10241914424489.2172257061659700.69305922424351.759167289
1659755.34714939424300.0145201141659833.80827856 424237.92474929
1659887.56604506424185.192899366 1660004.8584614424044.622970526
#Sta/Elev= 30
       0 1190.27    21.8 1180.83    63.6 1165.27   121.8 1147.01   154.3 1135.26
   161.4 1130.96   170.4 1121.83   192.6 1120.24   209.6  1108.5     235 1096.07
   245.1 1093.74   260.5 1092.29   297.5 1091.35   311.8 1089.83   321.1 1089.05
  326.951089.919     334 1094.59   340.4 1101.46   345.2  1105.2   365.2 1115.35
   391.3 1124.31   433.7 1143.07   462.1 1151.89   473.4  1153.8   494.8 1163.15
   524.5 1173.24   544.4 1181.21   555.7 1188.35   580.1 1201.04     616    1212
#Mann= 5 ,-1,0
       0      .1       0      90     .06       0  232.23      .1       0
   311.8    .045       0  326.95      .1       0
Bank Sta=311.8,326.95
XS Rating Curve= 0 ,0
Exp/Cntr(USF)=0,0
Exp/Cntr=0.3,0.1

Type RM Length L Ch R = 1 ,3103    ,415.3,421.5,423.1
XS GIS Cut Line= 6
1660041.40353835424757.8286038341660071.95859534424667.280556589
1660085.74498509424580.5559924991660088.47627884424505.602402255
1660099.02350184424404.4654654261660175.55287634424152.948251918
#Sta/Elev= 30
       0 1174.52    60.5 1154.55    77.4 1150.07   129.5 1129.56   150.5 1122.76
   171.2 1110.04   187.4 1110.69   195.4 1108.78   211.4 1095.65   227.4 1087.59
   291.6 1087.47  298.74 1084.96   303.7 1084.17   311.7 1084.97   335.9 1086.63
     352  1090.7     356 1092.64   367.4 1102.83   380.8 1110.73   396.6 1116.35
   422.3 1122.85   451.6 1139.32   480.8  1150.2   489.2 1152.03   510.1 1163.25
   543.7 1173.93   564.7 1182.23     594 1197.53   610.8 1201.96     623 1207.88
#Mann= 5 ,-1,0
       0      .1       0   95.56     .06       0  253.38      .1       0
  298.74    .045       0   311.7      .1       0
Bank Sta=298.74,311.7
XS Rating Curve= 0 ,0
Exp/Cntr(USF)=0,0
Exp/Cntr=0.3,0.1

Type RM Length L Ch R = 1 ,2682    ,74.8,75.4,75.2
XS GIS Cut Line= 3
1660295.31646188424925.2798442791660333.63055858424791.798475121
  1660637.671455424425.960648542
#Sta/Elev= 30
       0 1127.92    31.9 1124.37    75.4 1116.44    88.2  1112.6     109 1104.35
   117.6 1099.97   133.4 1094.15   138.1  1091.7   143.1 1090.54   154.3 1091.15
   163.9 1090.65     177 1086.73   185.6 1085.69   230.4 1083.23   296.3 1080.98
   306.8 1078.42   313.4 1077.87     318 1078.42   336.8 1086.57   356.4 1100.89
   367.3 1109.78   381.5 1117.08   390.1 1119.49   430.6 1136.25     476 1151.05
   523.6 1169.59   533.2 1172.38   557.7 1177.63   574.6 1183.14   614.6 1202.13
#Mann= 5 ,-1,0
       0      .1       0     120     .06       0  238.87      .1       0
   306.8    .045       0     318      .1       0
Bank Sta=306.8,318
XS Rating Curve= 0 ,0
Exp/Cntr(USF)=0,0
Exp/Cntr=0.3,0.1

Type RM Length L Ch R = 1 ,2606    ,499.3,496,491.3
XS GIS Cut Line= 6
1660291.91156751 424951.115618841660455.96045201424754.260041416
1660526.18964225424680.5508712531660581.19510968424624.400721088
1660636.63594368424550.9704217611660691.42290759424470.134953499
#Sta/Elev= 30
       0 1131.99    50.2  1134.8    75.3  1134.1   100.3 1130.83   112.7 1127.93
     144 1116.89     170 1105.24   175.2 1102.16   186.6 1092.82   206.5 1092.53
   211.6 1091.41     222 1086.64   250.2 1080.72   262.3  1079.6   297.1 1079.32
   305.7 1076.61   313.9 1075.56  320.78 1076.61   326.1 1079.81   341.5 1084.07
   359.4 1093.84   406.5 1113.55   423.7 1119.38   496.6 1149.16   534.9 1160.89
     542 1161.68   556.3 1160.12   576.1 1167.38   604.1 1175.76   626.3 1185.73
#Mann= 4 ,-1,0
       0      .1       0  123.75     .06       0   305.7    .045       0
  320.78      .1       0
Bank Sta=305.7,320.78
XS Rating Curve= 0 ,0
Exp/Cntr(USF)=0,0
Exp/Cntr=0.3,0.1

Type RM Length L Ch R = 1 ,2110    ,365.9,369,372.2
XS GIS Cut Line= 6
  1660869.132854425188.3014961781660895.26436342425097.979498342
1660919.83321193425013.9445614221660939.73441884424941.619574845
1660964.45385759424844.7227870081661027.79657868424596.425383344
#Sta/Elev= 30
       0 1153.03    24.7 1148.71    45.6 1142.23    53.9 1138.87    62.2 1132.97
    74.7 1125.99    87.2 1123.31   112.2 1107.21   137.2 1087.35     141 1085.44
   153.9 1086.41   160.4 1085.72   178.9  1077.6   203.8 1073.84   261.8 1071.43
     294 1071.73     299 1070.27   307.2 1068.93  316.281070.226   319.6 1072.87
   323.8 1079.19   327.9 1084.13   336.1 1089.84   343.3 1093.84   389.8 1115.35
   414.6 1125.96   455.9  1139.4   521.9  1168.6   583.8 1190.15   612.8 1204.96
#Mann= 5 ,-1,0
       0      .1       0      90     .06       0  286.59      .1       0
     299    .045       0  316.28      .1       0
Bank Sta=299,316.28
XS Rating Curve= 0 ,0
Exp/Cntr(USF)=0,0
Exp/Cntr=0.3,0.1

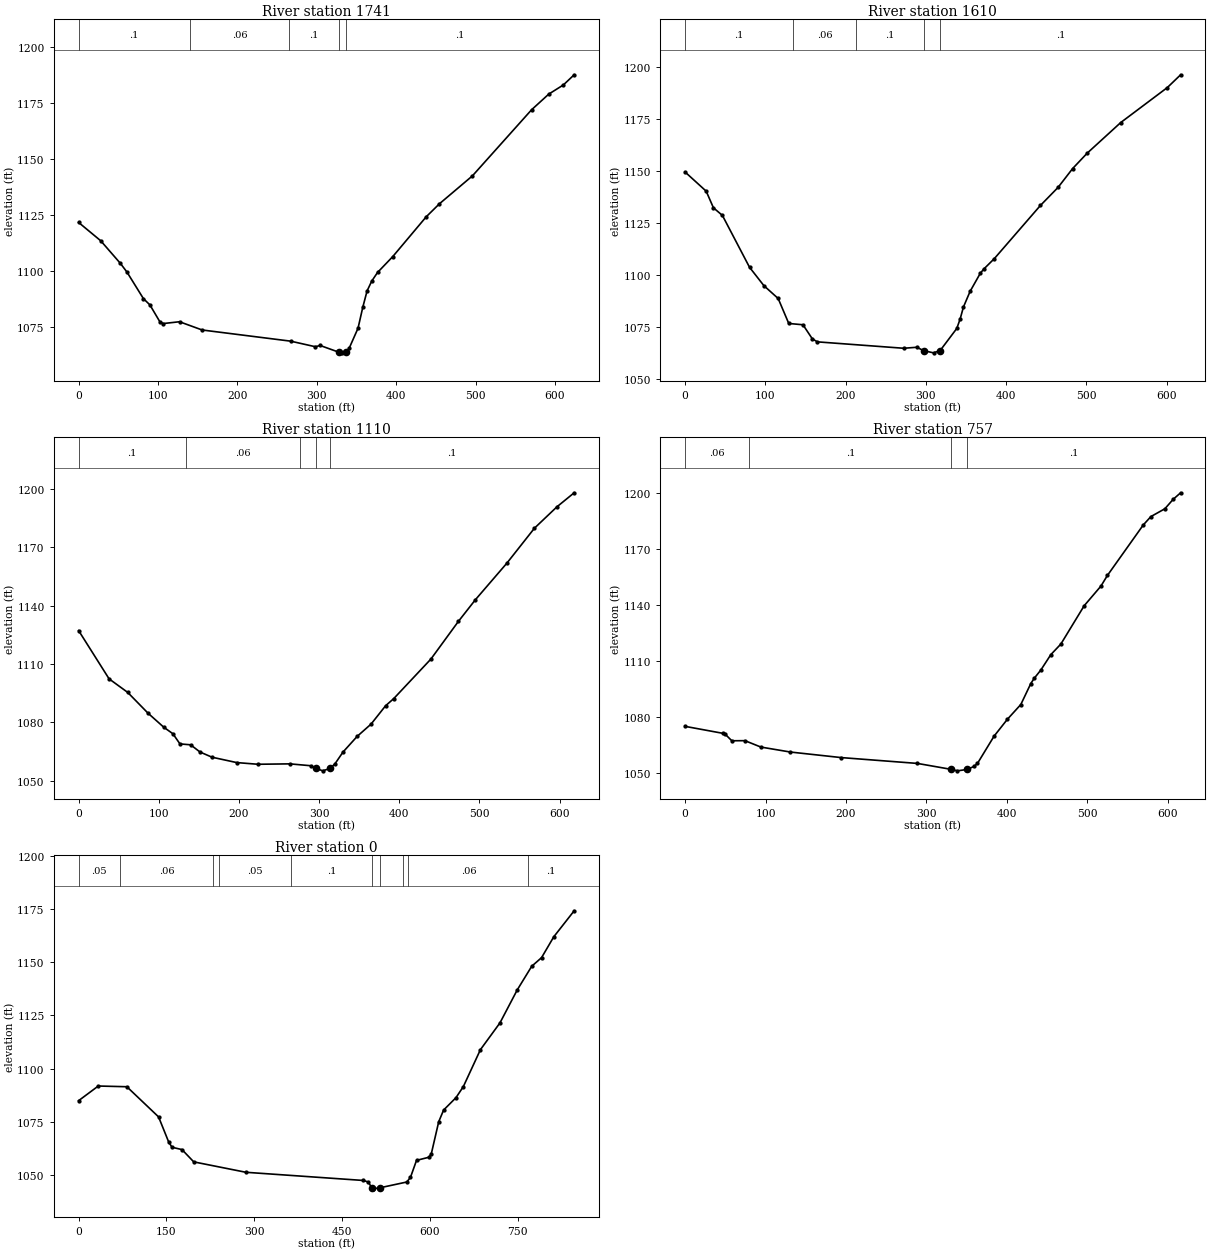
Type RM Length L Ch R = 1 ,1741    ,135.8,131,126.7
XS GIS Cut Line= 4
1661119.34108324425339.4119779621661158.98504988425188.945104579
1661297.73893311425039.3792304381661427.48282394424808.723424534
#Sta/Elev= 30
       0 1121.71    27.8 1113.57    52.6  1103.5    60.9 1099.62    81.6 1087.82
    89.8 1085.01   102.2 1077.59   106.4 1076.71   127.1 1077.52   155.6 1073.85
   267.1 1068.88   298.2  1066.4   304.3 1066.95   327.8 1063.97   332.2 1063.68
  336.76 1063.97   340.7 1065.62     352 1074.64     358 1083.98   363.4 1091.25
   369.3 1095.63   376.6 1099.46   395.8 1106.54   437.9 1124.23   454.5 1130.01
     496 1142.41   570.6 1171.85   592.3 1178.84   610.7 1182.92   624.3 1187.44
#Mann= 5 ,-1,0
       0      .1       0     140     .06       0   265.6      .1       0
   327.8    .045       0  336.76      .1       0
Bank Sta=327.8,336.76
XS Rating Curve= 0 ,0
Exp/Cntr(USF)=0,0
Exp/Cntr=0.3,0.1

Type RM Length L Ch R = 1 ,1610    ,497.6,500,501.5
XS GIS Cut Line= 6
1661258.80563109425419.8945369271661339.98886767425256.179641262
1661368.18270892425186.1988100861661394.05372018425089.603530839
1661423.17144409425019.9625940021661515.52066883   424861.006219
#Sta/Elev= 30
       0 1149.29    26.3 1140.07    35.3  1132.1    46.5 1128.42    80.3 1103.49
    98.2 1094.65     116 1088.48   129.2 1076.47   146.9 1075.85   158.6 1069.06
   164.9 1067.63   272.4 1064.55   288.9 1065.03   297.2  1063.4   309.6 1062.35
   317.9 1063.46   338.6 1074.07   342.8 1078.63   346.9 1084.38   355.2 1091.91
     368 1100.66   372.4 1102.69   385.4 1107.65   442.8  1133.2   464.8 1141.88
     483 1150.96   501.2 1158.38     543  1173.1     601  1189.9   617.6 1196.05
#Mann= 5 ,-1,0
       0      .1       0  134.52     .06       0  212.76      .1       0
   297.2    .045       0   317.9      .1       0
Bank Sta=297.2,317.9
XS Rating Curve= 0 ,0
Exp/Cntr(USF)=0,0
Exp/Cntr=0.3,0.1

Type RM Length L Ch R = 1 ,1110    ,354.9,353.3,352
XS GIS Cut Line= 6
1661689.02721159425646.8901459281661766.31478667425482.944607675
1661840.93668467425324.6519452481661871.77290909425256.261334002
 1661903.3673341425171.7949675021661934.51064451  425080.2045995
#Sta/Elev= 30
       0 1127.17      38 1102.35    61.2  1095.4    86.6 1084.69   106.3 1077.45
   117.6 1074.13   126.4  1068.9   139.7 1068.44   151.4 1064.74   166.4 1062.06
   197.2  1059.3   223.7 1058.43   263.5 1058.64     290 1057.66  295.861056.347
   304.6 1055.05   313.6 1056.31   319.7 1058.61   329.8  1064.7   347.5 1072.78
   364.8 1079.08   382.9  1088.5   393.2 1092.24   439.5 1112.55   473.7 1131.87
     495 1143.06   534.1 1161.78   568.7 1179.86   596.7 1190.83   618.2 1198.05
#Mann= 5 ,-1,0
       0      .1       0  133.75     .06       0  276.25      .1       0
  295.86    .045       0   313.6      .1       0
Bank Sta=295.86,313.6
XS Rating Curve= 0 ,0
Exp/Cntr(USF)=0,0
Exp/Cntr=0.3,0.1

Type RM Length L Ch R = 1 ,757     ,733.7,756.8,756.5
XS GIS Cut Line= 6
1662057.89574675425770.6774140511662092.12107201425682.916106633
1662120.03341774425599.8280182091662185.58971709425358.576204128
1662208.89413242425273.8339195461662225.03287966425178.856747291
#Sta/Elev= 30
       0 1075.14    46.6 1071.45    49.7 1071.01    58.1 1067.44    74.4  1067.5
    94.2 1064.08   130.8 1061.43   193.6 1058.48   288.9 1055.34  331.161052.143
   338.6 1051.38   350.8 1052.13   359.4 1053.78   363.5 1055.34   384.2 1069.94
   400.8 1078.98   417.4 1086.81   429.8    1098     434 1100.79   442.3 1105.24
   454.7 1113.45   467.2 1119.12   496.2  1139.6     517 1150.07   525.1  1155.8
   569.7 1182.77   579.1 1187.21   596.5 1191.39   606.9 1196.47   616.1 1199.93
#Mann= 4 ,-1,0
       0     .06       0      80      .1       0  331.16    .045       0
   350.8      .1       0
Bank Sta=331.16,350.8
XS Rating Curve= 0 ,0
Exp/Cntr(USF)=0,0
Exp/Cntr=0.3,0.1

Type RM Length L Ch R = 1 ,0       ,156.2,165.6,165.3
BEGIN DESCRIPTION:
Structure 2 XS 4
END DESCRIPTION:
XS GIS Cut Line= 6
1662141.71367591425837.0652111811662402.59798499425645.468938437
1662641.04203984 425707.139041171662721.37652484425733.504473999
1662811.45639718425760.2015990911662905.24787626425789.598850012
#Sta/Elev= 30
       0 1084.85    33.6 1091.75    82.4 1091.41   136.6  1077.2   153.7 1065.49
   159.5 1062.89   176.6 1061.79   196.7    1056   285.9 1051.09   486.4 1047.24
   494.9 1046.52  500.911043.819   502.9 1043.29   514.6 1043.77   560.8 1046.51
   567.1 1048.73   577.4 1056.71   598.9  1058.2   602.7 1059.84   615.3  1074.9
   623.7 1080.43   644.8 1086.25   657.4 1091.47   686.6 1108.89     720 1121.51
   749.6 1137.09   774.3  1148.2   791.1 1152.26     812  1162.1   846.8 1174.34
#Mann= 10 ,-1,0
       0     .05       0      70     .06       0     230      .1       0
     240     .05       0  363.68      .1       0  500.91    .045       0
   514.6      .1       0  553.68     .05       0  563.68     .06       0
  768.47      .1       0
Bank Sta=500.91,514.6
XS Rating Curve= 0 ,0
Exp/Cntr=0.3,0.1
LCMann Table=0

Chan Stop Cuts=-1
Use User Specified Reach Order=0
Composite Channel Slope=5